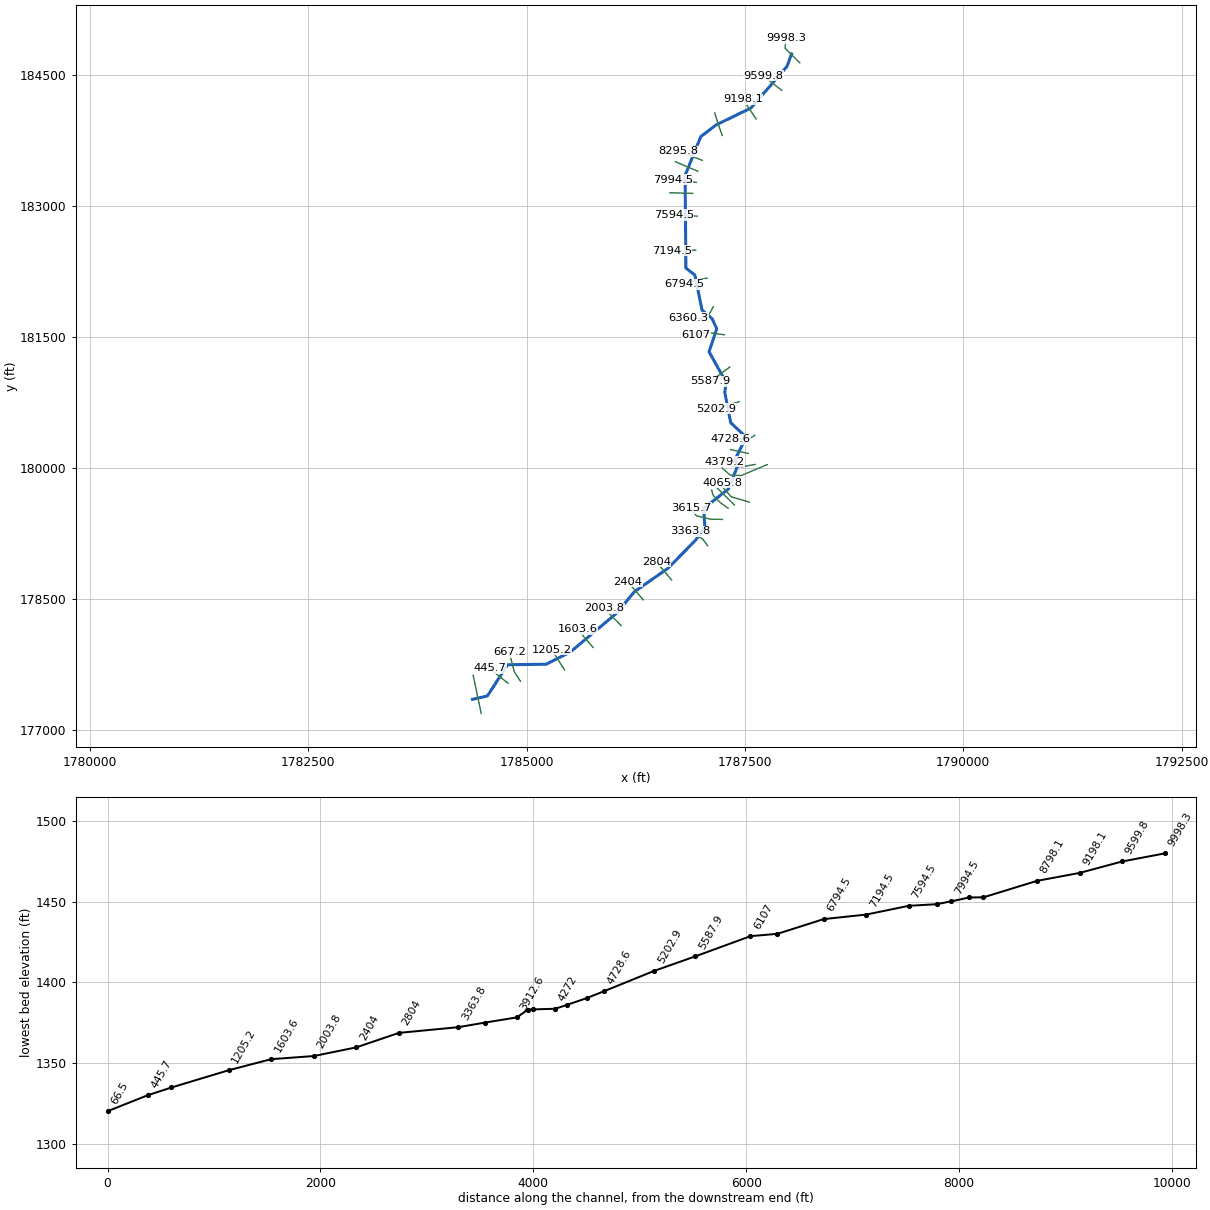
--- Davy Branch.prj (project) ---

Proj Title=Davy Branch
Current Plan=p01
Default Exp/Contr=0,0
English Units
Geom File=g01
Flow File=f01
Plan File=p01
BEGIN DESCRIPTION:
END DESCRIPTION:
DSS Export Rating Curves= 0
DSS Export Rating Curve Sorted= 0
DSS Export Volume Flow Curves= 0
DXF OffsetX= 0
DXF OffsetY= 0
DXF ScaleX= 0
DXF ScaleY= 0

--- Davy Branch.p01 (plan) ---

Plan Title=Floodplain
Program Version=4.00
Geom File=g01
Flow File=f01
K Sum by GR=0
Std Step Tol=0.01
Critical Tol=0.01
Num of Std Step Trials=20
Max Error Tol=0.3
Flow Tol Ratio=0.001
Split Flow NTrial=30
Split Flow Tol=0.02
Split Flow Ratio=0.02
Log Output Level=0
Friction Slope Method=1
Unsteady Friction Slope Method=2
Unsteady Bridges Friction Slope Method=1
Global Log Level=0
CheckData=False
Run HTab=0
Run UNet=0
Run PostProcess=0
UNET Theta=0
UNET Theta Warmup=0
UNET ZTol=0
UNET ZSATol=0
UNET MxIter=0
UNET MaxInSteps=0
UNET DtIC=0
UNET DtMin=0
UNET MaxCRTS=0
UNET WFStab=0
UNET SFStab=0
UNET WFX=0
UNET SFX=0
UNET DSS MLevel=0
UNET DZMax Abort=0
UNET Convert EG Bridges=0
UNET Use Existing IB Tables=0
UNET Froude Limit=0
UNET Froude Power=0
Write IC File=0
Echo Input=False
Echo Output=False
Write Detailed=0

--- Davy Branch.f01 (steady flow) ---

Flow Title=NFF Regression Equation
Program Version=4.00
Number of Profiles=1
Profile Names=P100yr
River Rch & RM=Davy Branch,Main      ,9998.3
627.9892
River Rch & RM=Davy Branch,Main      ,8161.1
661.5675
River Rch & RM=Davy Branch,Main      ,7854.4
757.6883
River Rch & RM=Davy Branch,Main      ,6360.3
829.7510
River Rch & RM=Davy Branch,Main      ,4566.4
886.3207
River Rch & RM=Davy Branch,Main      ,4272
1024.326
River Rch & RM=Davy Branch,Main      ,3363.8
1052.022
River Rch & RM=Davy Branch,Main      ,667.2
1150.016
Boundary for River Rch & Prof#=Davy Branch,Main      ,1
Up Type=0
Dn Type=3
Dn Slope=0.020068

--- Davy Branch.g01 (geometry) ---

Geom Title=Geometry
Program Version=4.00

River Reach=Davy Branch     ,Main
Reach XY= 30
     1788033.922      184738.275     1787980.703       184595.27
     1787568.121      184118.737     1787168.866      183925.904
     1786994.661      183792.608     1786814.287      183347.687
     1786823.734       182285.65     1786926.269      182206.824
     1787008.189      181804.741     1787123.929      181705.536
     1787176.597      181592.649     1787088.606      181328.254
     1787286.265      180972.768     1787268.228      180866.047
     1787336.619       180515.07     1787513.987      180348.976
     1787390.478      180100.439     1787413.278      180012.278
      1787308.06      179755.246     1787026.978      179532.786
     1787040.506      179320.095     1786930.779      179166.026
      1786617.66      178847.815     1786232.583       178579.06
     1786030.325      178333.971     1785502.443      177891.534
     1785223.994      177749.342     1784782.078       177743.33
       1784549.3       177385.53     1784378.946      177347.428

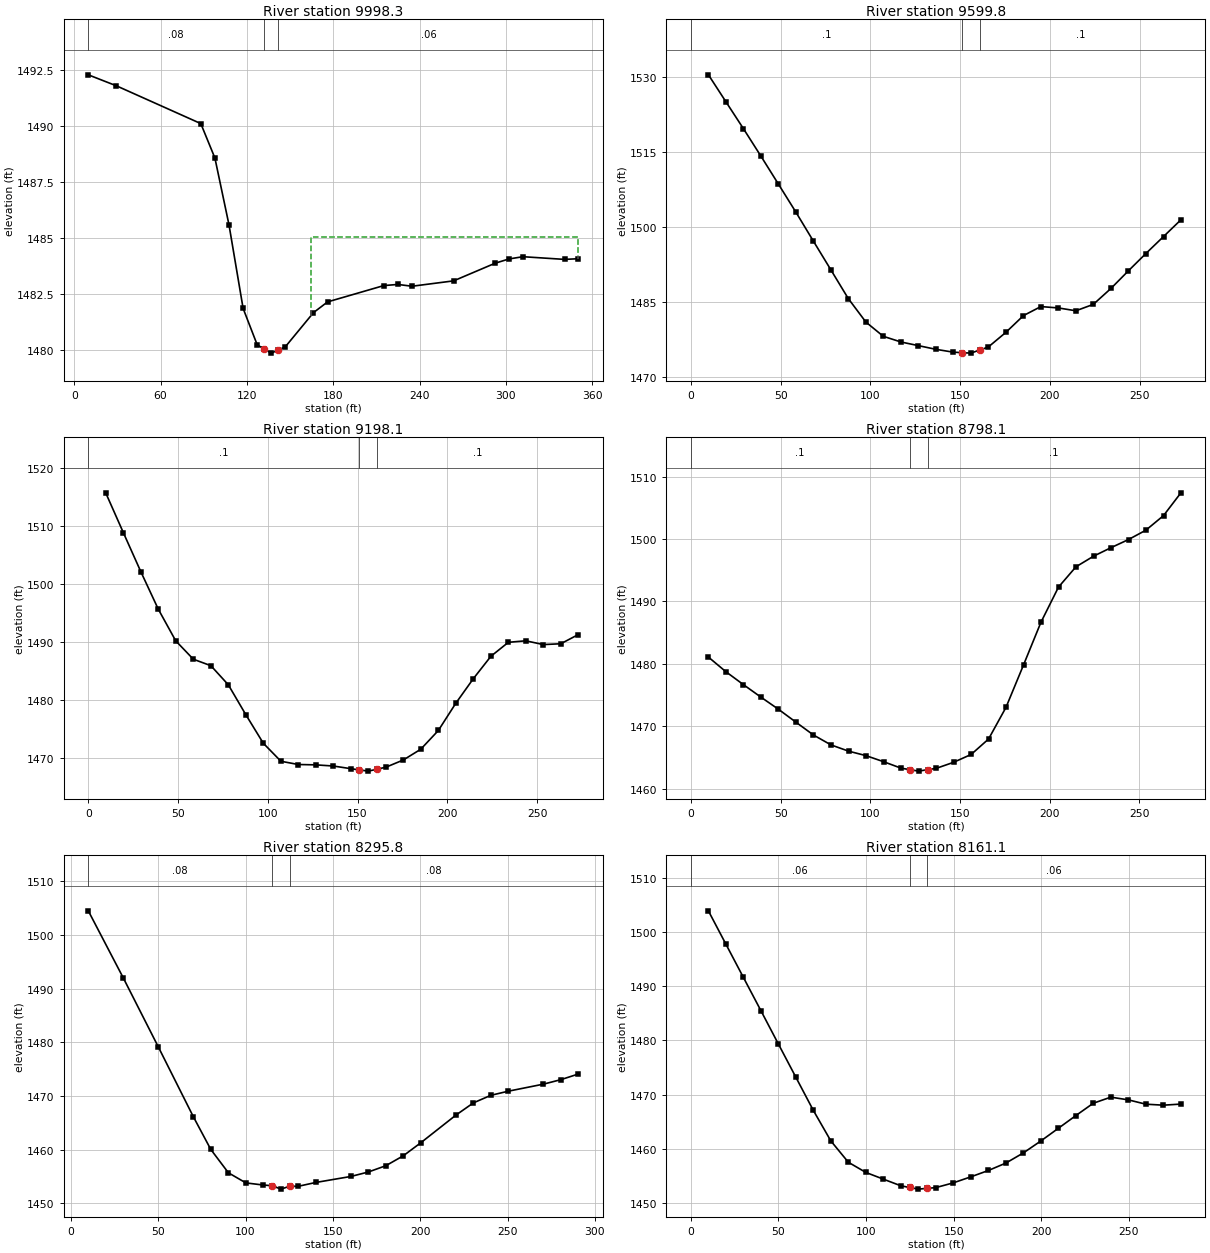
Type RM Length L Ch R = 1 ,9998.3  ,395.6,398.5,401.4
XS GIS Cut Line= 3
     1788127.579      184637.413      1787960.23      184802.051
     1787967.281      184917.485
#Sta/Elev= 22
     9.8 1492.28    29.3 1491.79      88  1490.1    97.8 1488.56   107.6 1485.57
   117.4 1481.84   127.2 1480.21   131.9 1480.03   136.9 1479.84   141.9 1479.98
   146.7 1480.12   166.3 1481.65   176.1 1482.13   215.2 1482.86     225 1482.91
   234.8 1482.83   263.7 1483.07   292.6 1483.86   302.2 1484.05   311.9 1484.15
   340.8 1484.03   350.4 1484.06
#Mann= 3 , 0 , 0
     9.8     .08       0   131.9    .045       0   141.9     .06       0
#XS Ineff= 2 , 0
                          164.43         1485.03
Permanent Ineff=
       F       F
Bank Sta=131.9,141.9
XS Rating Curve= 0 ,0
Exp/Cntr=0.3,0.1

Type RM Length L Ch R = 1 ,9599.8  ,407.9,401.7,395.5
XS GIS Cut Line= 3
     1787921.782      184319.862     1787815.273      184405.231
     1787708.763      184490.601
#Sta/Elev= 30
     9.8 1530.45    19.5 1525.09    29.3 1519.69      39 1514.23    48.7 1508.67
    58.5 1503.03    68.2 1497.27      78  1491.5    87.7 1485.76    97.5 1481.07
   107.2 1478.22     117 1477.09   126.7 1476.36   136.5 1475.62   146.2 1475.05
     151 1474.96     156 1474.86     161 1475.49   165.7 1476.08   175.5 1479.01
   185.3 1482.36     195 1484.16   204.8 1483.88   214.5 1483.32   224.2  1484.6
     234 1487.77   243.8 1491.32   253.5 1494.76   263.3 1498.14     273 1501.49
#Mann= 3 , 0 , 0
       0      .1       0     151    .045       0     161      .1       0
Bank Sta=151,161
XS Rating Curve= 0 ,0
Exp/Cntr=0.3,0.1

Type RM Length L Ch R = 1 ,9198.1  ,405,400,394.1
XS GIS Cut Line= 3
       1787627.6      183994.236     1787551.404       184107.49
     1787475.208      184220.744
#Sta/Elev= 30
     9.7 1515.69    19.5 1508.85    29.3 1502.08      39 1495.64    48.7  1490.2
    58.5 1487.03    68.3 1485.91      78 1482.62    87.7  1477.5    97.5 1472.55
   107.3 1469.45     117 1468.89   126.7 1468.83   136.5 1468.63   146.3 1468.17
     151 1467.96     156 1467.75     161 1468.09   165.8 1468.43   175.5 1469.67
   185.2 1471.52     195 1474.75   204.7 1479.43   214.5 1483.68   224.3 1487.54
     234 1489.94   243.7  1490.2   253.5 1489.55   263.2 1489.69     273 1491.28
#Mann= 3 , 0 , 0
       0      .1       0     151    .045       0     161      .1       0
Bank Sta=151,161
XS Rating Curve= 0 ,0
Exp/Cntr=0.3,0.1

Type RM Length L Ch R = 1 ,8798.1  ,484.4,502.3,521.1
XS GIS Cut Line= 3
     1787239.845      183804.908     1787193.999      183933.644
     1787153.832      184064.072
#Sta/Elev= 30
     9.8 1481.09    19.5 1478.76    29.3 1476.68      39 1474.69    48.8 1472.74
    58.6 1470.66    68.3 1468.62    78.1 1467.03    87.9 1466.03    97.6 1465.31
   107.4 1464.34   117.1 1463.31   121.9 1463.07   126.9 1462.83   131.9 1463.06
   136.7 1463.27   146.4 1464.24   156.2  1465.5   165.9 1467.97   175.6 1473.03
   185.4 1479.84   195.1 1486.67   204.9 1492.31   214.6 1495.55   224.4 1497.25
   234.1 1498.61   243.9 1499.92   253.6 1501.42   263.4 1503.75   273.1  1507.4
#Mann= 3 , 0 , 0
       0      .1       0   121.9    .045       0   131.9      .1       0
Bank Sta=121.9,131.9
XS Rating Curve= 0 ,0
Exp/Cntr=0.3,0.1

Type RM Length L Ch R = 1 ,8295.8  ,135.2,134.7,134.1
XS GIS Cut Line= 2
     1787011.796      183519.829      1786740.73      183624.293
#Sta/Elev= 25
      10 1504.49    30.1 1491.95    50.1 1479.13    70.1 1466.16    80.1 1460.06
    90.2  1455.7   100.2 1453.82   110.2 1453.42   115.2  1453.3   120.3 1452.66
   125.2 1453.19   130.2 1453.19   140.2  1453.9   160.3 1455.02   170.3 1455.85
   180.3 1457.02   190.3 1458.87   200.3 1461.29   220.4 1466.44   230.4 1468.72
   240.4 1470.13   250.4  1470.9   270.5 1472.21   280.5 1473.05   290.5  1474.1
#Mann= 3 , 0 , 0
      10     .08       0   115.2    .045       0   125.2     .08       0
Bank Sta=115.2,125.2
XS Rating Curve= 0 ,0
Exp/Cntr=0.3,0.1

Type RM Length L Ch R = 1 ,8161.1  ,160.9,166.6,172.2
XS GIS Cut Line= 2
     1786959.564      183395.553     1786702.007       183504.52
#Sta/Elev= 30
      10 1503.92      20 1497.77      30 1491.62      40 1485.48    49.9 1479.37
    59.9 1473.22    69.9 1467.08    79.9 1461.44    89.9  1457.5    99.9 1455.62
   109.9 1454.38   119.9 1453.15   124.8 1452.85   129.8 1452.54   134.8 1452.68
   139.8 1452.82   149.8  1453.7   159.8 1454.81   169.8 1455.98   179.8 1457.35
   189.8 1459.23   199.8 1461.44   209.7 1463.76   219.7 1466.11   229.7  1468.4
   239.7 1469.52   249.7 1469.02   259.7 1468.22   269.7 1468.04   279.7 1468.24
#Mann= 3 , 0 , 0
       0     .06       0   124.8    .045       0   134.8     .06       0
Bank Sta=124.8,134.8
XS Rating Curve= 0 ,0
Exp/Cntr=0.3,0.1

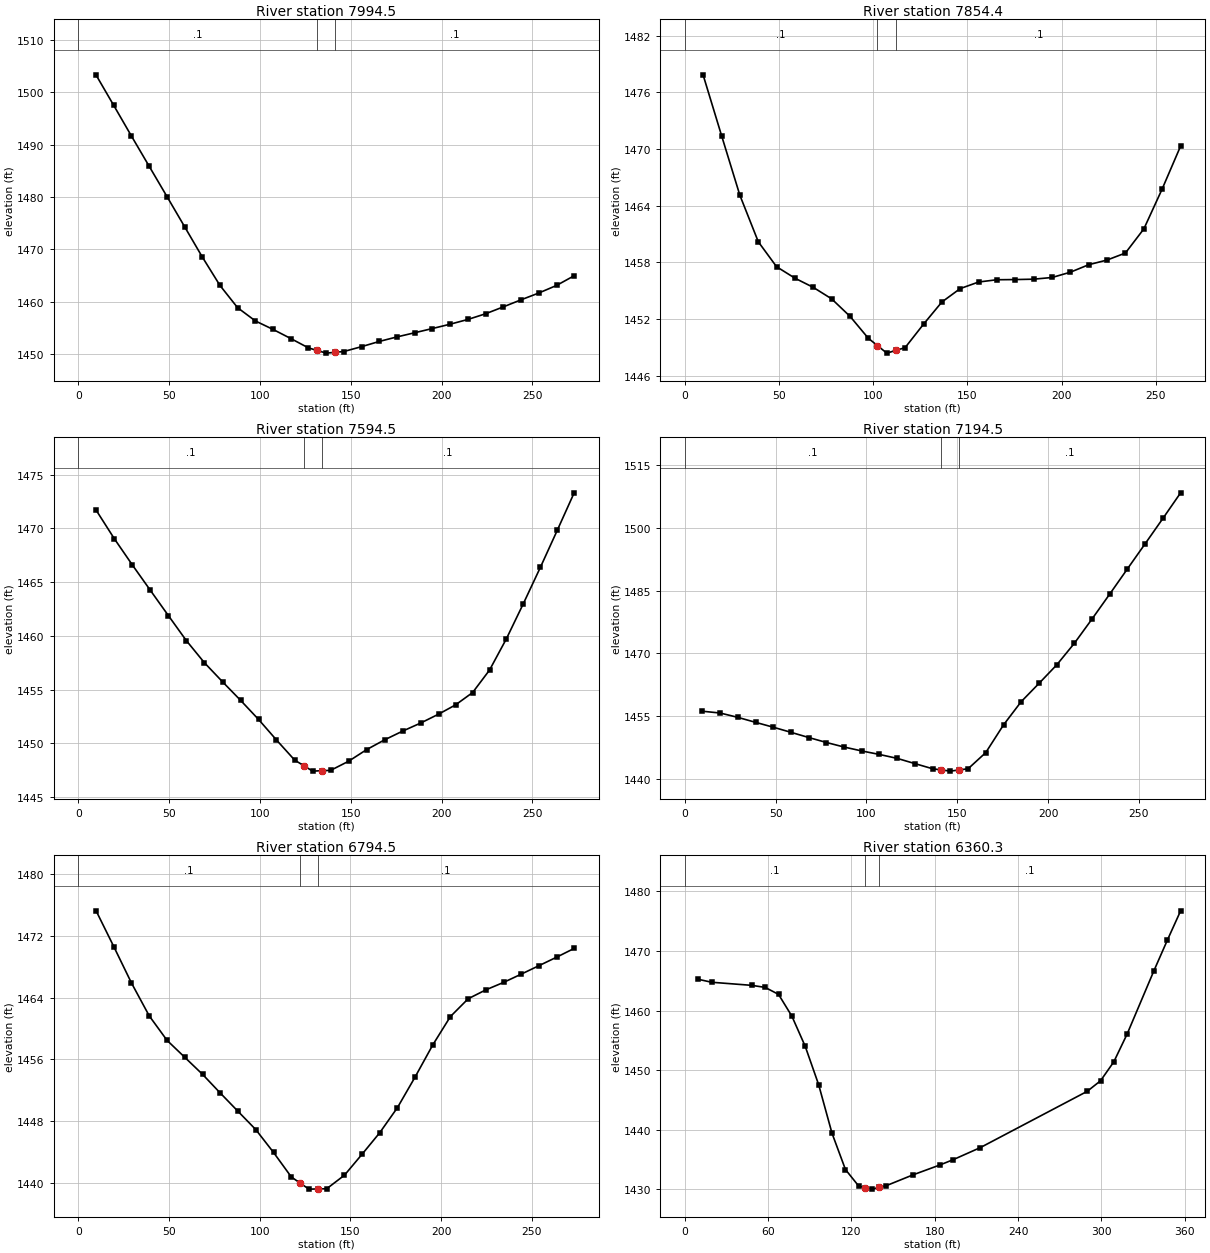
Type RM Length L Ch R = 1 ,7994.5  ,138.3,140.1,141.9
XS GIS Cut Line= 3
     1786942.264      183267.527     1786806.707      183283.547
     1786671.151      183299.568
#Sta/Elev= 30
     9.7  1503.3    19.5 1497.46    29.2 1491.64      39 1485.85    48.8 1480.07
    58.5 1474.32    68.2 1468.56      78 1463.09    87.7 1458.85    97.5 1456.32
   107.3 1454.69     117 1452.96   126.7 1451.18   131.5 1450.69   136.5 1450.18
   141.5 1450.34   146.2 1450.49     156 1451.42   165.8 1452.42   175.5 1453.28
   185.2 1454.07     195 1454.88   204.7  1455.7   214.5 1456.61   224.3  1457.7
     234 1459.01   243.7 1460.35   253.5 1461.65   263.3  1463.1     273 1464.95
#Mann= 3 , 0 , 0
       0      .1       0   131.5    .045       0   141.5      .1       0
Bank Sta=131.5,141.5
XS Rating Curve= 0 ,0
Exp/Cntr=0.3,0.1

Type RM Length L Ch R = 1 ,7854.4  ,260.3,259.9,259.5
XS GIS Cut Line= 2
     1786902.829      183141.597     1786639.868      183148.802
#Sta/Elev= 29
     9.7 1477.85    19.5 1471.42    29.2 1465.11      39 1460.17    48.7 1457.53
    58.5 1456.31    68.2 1455.34    77.9 1454.13    87.7 1452.27    97.4 1449.95
   102.2 1449.18   107.2 1448.38   112.2 1448.68   116.9 1448.96   126.7 1451.45
   136.4 1453.79   146.1 1455.21   155.9 1455.91   165.6 1456.15   175.4 1456.17
   185.1 1456.21   194.9 1456.39   204.6 1456.95   214.3 1457.74   224.1 1458.24
   233.8 1458.98   243.6 1461.54   253.3 1465.76   263.1 1470.31
#Mann= 3 , 0 , 0
       0      .1       0   102.2    .045       0   112.2      .1       0
Bank Sta=102.2,112.2
XS Rating Curve= 0 ,0
Exp/Cntr=0.3,0.1

Type RM Length L Ch R = 1 ,7594.5  ,398.5,400,401.4
XS GIS Cut Line= 3
     1786956.042      182880.988     1786757.841      182890.344
     1786683.346      182893.871
#Sta/Elev= 30
     9.9 1471.68    19.8 1469.05    29.8 1466.59    39.7 1464.23    49.6 1461.88
    59.5 1459.55    69.4  1457.5    79.4 1455.72    89.3    1454    99.2 1452.22
   109.1  1450.3   119.1 1448.43     124 1447.92     129  1447.4     134 1447.44
   138.9 1447.47   148.8 1448.32   158.7  1449.4   168.7 1450.32   178.6 1451.13
   188.5 1451.88   198.4 1452.71   207.7 1453.57   217.1 1454.72   226.4 1456.81
   235.7 1459.73     245 1462.99   254.4 1466.38   263.7 1469.83     273 1473.32
#Mann= 3 , 0 , 0
       0      .1       0     124    .045       0     134      .1       0
Bank Sta=124,134
XS Rating Curve= 0 ,0
Exp/Cntr=0.3,0.1

Type RM Length L Ch R = 1 ,7194.5  ,396.9,400,404.3
XS GIS Cut Line= 3
     1786935.433      182492.013     1786798.976      182488.601
     1786662.519       182485.19
#Sta/Elev= 30
     9.7 1456.24    19.5 1455.81    29.2 1454.78      39 1453.59    48.8 1452.42
    58.5 1451.21    68.2 1449.98      78 1448.79    87.7 1447.71    97.5 1446.77
   107.2 1445.94     117    1445   126.7 1443.76   136.5 1442.53   141.2 1442.26
   146.2 1441.97   151.2 1442.26     156 1442.54   165.7 1446.38   175.5 1452.99
   185.2 1458.51     195 1462.86   204.8 1467.29   214.5 1472.43   224.2  1478.2
     234 1484.17   243.7 1490.15   253.5 1496.16   263.3 1502.21     273 1508.27
#Mann= 3 , 0 , 0
       0      .1       0   141.2    .045       0   151.2      .1       0
Bank Sta=141.2,151.2
XS Rating Curve= 0 ,0
Exp/Cntr=0.3,0.1

Type RM Length L Ch R = 1 ,6794.5  ,430.6,434.2,436.5
XS GIS Cut Line= 3
     1787066.416      182172.115     1786932.834      182142.104
      1786802.16      182102.902
#Sta/Elev= 30
     9.8 1475.28    19.6 1470.61    29.3 1465.91    39.1 1461.64    48.9 1458.47
    58.7 1456.26    68.5 1454.05    78.2 1451.64      88 1449.26    97.8 1446.89
   107.6 1443.92   117.4 1440.74   122.1 1439.97   127.1 1439.16   132.1 1439.18
   136.9 1439.21   146.7 1440.97   156.4 1443.69   166.1 1446.47   175.9 1449.74
   185.6  1453.7   195.4 1457.89   205.1 1461.56   214.9 1463.87   224.6 1465.02
   234.4 1465.99   244.1 1467.06   253.8 1468.15   263.6 1469.26   273.3  1470.4
#Mann= 3 , 0 , 0
       0      .1       0   122.1    .045       0   132.1      .1       0
Bank Sta=122.1,132.1
XS Rating Curve= 0 ,0
Exp/Cntr=0.3,0.1

Type RM Length L Ch R = 1 ,6360.3  ,264.3,253.4,242.4
XS GIS Cut Line= 4
     1787137.873      181844.803     1787086.542      181752.047
     1786990.183      181706.119     1786846.095      181715.124
#Sta/Elev= 26
     9.6 1465.25    19.3 1464.75    48.2 1464.23    57.8 1463.89    67.5 1462.72
    77.1 1459.07    86.7 1454.02    96.4 1447.57     106 1439.44   115.7 1433.34
   125.4 1430.52   130.1 1430.29   135.1 1430.05   140.1 1430.33   144.8  1430.6
   164.2 1432.43   183.6 1434.09   193.3 1434.99   212.8 1437.01   289.8 1446.45
   299.4 1448.22     309 1451.41   318.6 1456.08   337.9  1466.7   347.5 1471.79
   357.1 1476.73
#Mann= 3 , 0 , 0
       0      .1       0   130.1    .045       0   140.1      .1       0
Bank Sta=130.1,140.1
XS Rating Curve= 0 ,0
Exp/Cntr=0.3,0.1

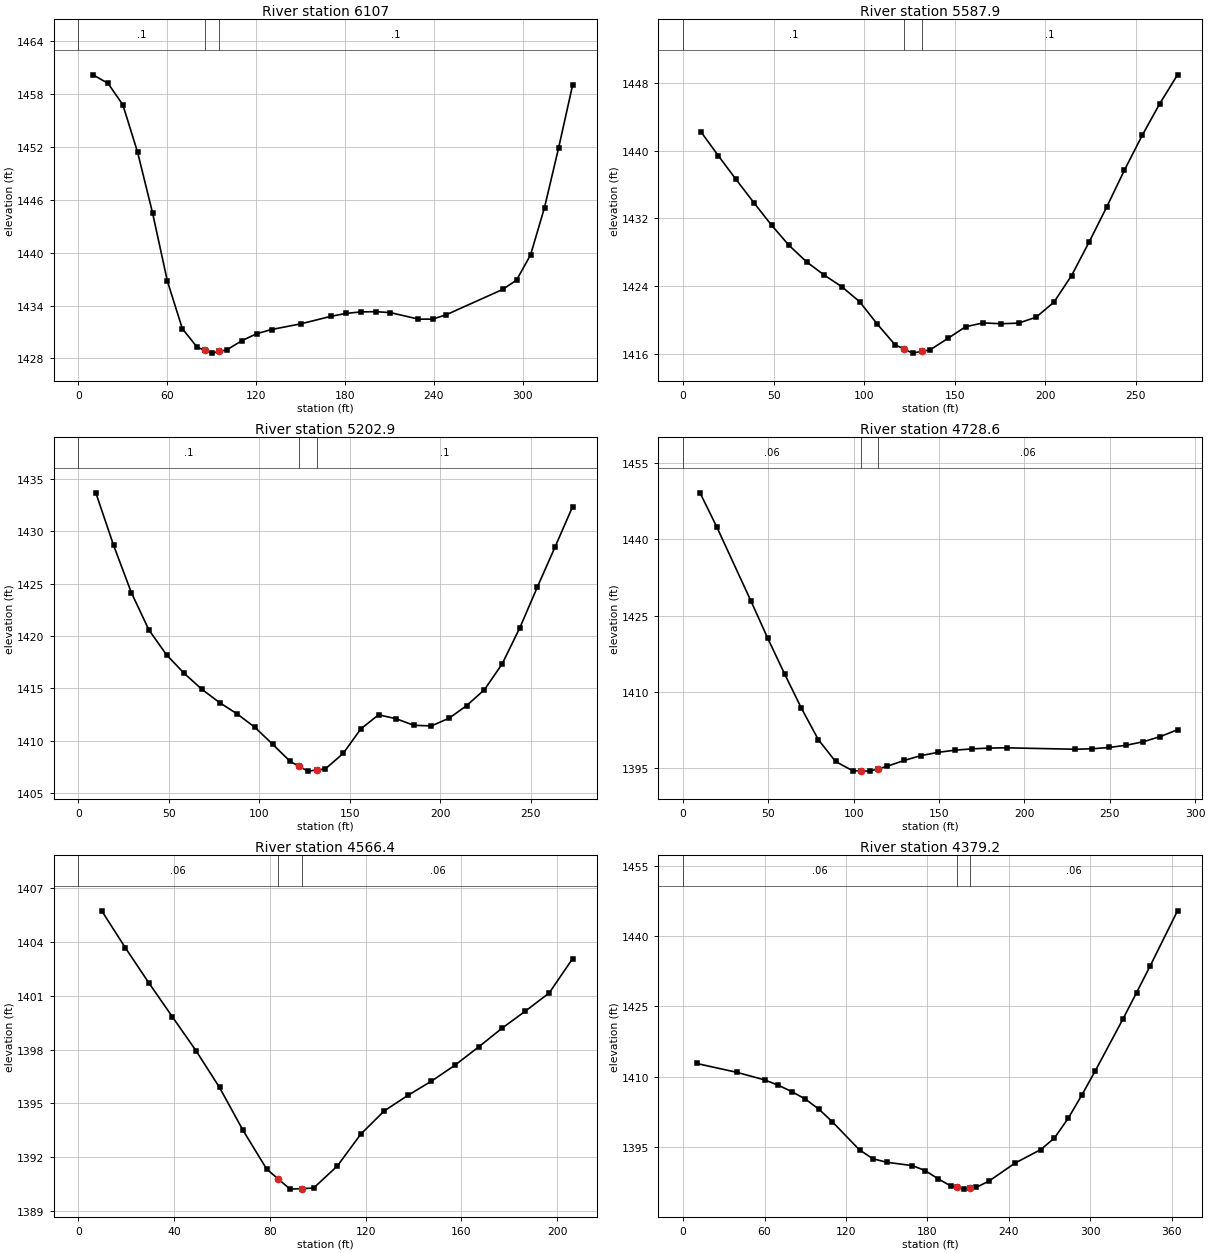
Type RM Length L Ch R = 1 ,6107    ,503.4,519.1,534.7
XS GIS Cut Line= 3
     1787263.951      181522.406     1787055.023      181550.323
     1786935.249      181522.406
#Sta/Elev= 30
      10 1460.21    20.1 1459.24    30.1 1456.81    40.1 1451.39    50.2  1444.5
    60.2 1436.76    70.3 1431.37    80.3 1429.27    85.3 1428.93    90.3  1428.6
    95.3 1428.79   100.4 1428.98   110.4 1430.01   120.4  1430.8   130.5 1431.28
   150.6 1431.94   170.6 1432.78   180.7 1433.11   190.7 1433.28   200.7 1433.31
   210.8  1433.2   229.7 1432.46   239.2 1432.46   248.6 1432.97   286.5 1435.83
   295.9 1436.89   305.4 1439.76   314.8 1445.13   324.3 1451.89   333.8 1459.06
#Mann= 3 , 0 , 0
       0      .1       0    85.3    .045       0    95.3      .1       0
Bank Sta=85.3,95.3
XS Rating Curve= 0 ,0
Exp/Cntr=0.3,0.1

Type RM Length L Ch R = 1 ,5587.9  ,392.9,385,377.2
XS GIS Cut Line= 3
     1787326.359      181153.473     1787216.798      181072.057
     1787107.237       180990.64
#Sta/Elev= 30
     9.8 1442.22    19.5 1439.37    29.2 1436.59      39 1433.86    48.8 1431.19
    58.5  1428.8    68.2 1426.85      78 1425.28    87.7 1423.91    97.5 1422.14
   107.2 1419.51     117 1417.07   121.8 1416.58   126.7 1416.08   131.8 1416.29
   136.5 1416.48   146.2 1417.82     156  1419.2   165.7 1419.65   175.5 1419.55
   185.2 1419.62     195 1420.33   204.8 1422.11   214.5 1425.24   224.2  1429.2
     234 1433.38   243.7 1437.69   253.5 1441.79   263.2 1445.54     273 1448.94
#Mann= 3 , 0 , 0
       0      .1       0   121.8    .045       0   131.8      .1       0
Bank Sta=121.8,131.8
XS Rating Curve= 0 ,0
Exp/Cntr=0.3,0.1

Type RM Length L Ch R = 1 ,5202.9  ,480.1,474.2,468.4
XS GIS Cut Line= 3
     1787432.041      180755.552     1787301.345      180716.172
     1787170.649      180676.792
#Sta/Elev= 30
     9.7 1433.66    19.5 1428.66    29.3 1424.15      39 1420.59    48.8  1418.2
    58.5 1416.44    68.3 1414.92      78 1413.66    87.8 1412.57    97.5  1411.3
   107.3 1409.69     117 1408.05   121.8 1407.59   126.8 1407.12   131.8 1407.23
   136.5 1407.34   146.3 1408.81     156 1411.14   165.8 1412.49   175.5 1412.12
   185.3 1411.49     195 1411.43   204.8 1412.17   214.5 1413.37   224.3 1414.89
     234 1417.32   243.8 1420.77   253.5 1424.67   263.3  1428.5     273 1432.35
#Mann= 3 , 0 , 0
       0      .1       0   121.8    .045       0   131.8      .1       0
Bank Sta=121.8,131.8
XS Rating Curve= 0 ,0
Exp/Cntr=0.3,0.1

Type RM Length L Ch R = 1 ,4728.6  ,166.7,162.2,157.7
XS GIS Cut Line= 3
     1787613.364      180371.501     1787545.823      180330.076
     1787335.387      180324.551
#Sta/Elev= 27
     9.9 1449.14    19.8 1442.37    39.6 1427.98    49.5 1420.62    59.4 1413.59
    69.3 1406.82    79.2 1400.65    89.3 1396.35    99.3 1394.53   104.3 1394.49
   109.3 1394.45   114.3 1394.91   119.3 1395.37   129.4 1396.54   139.4  1397.5
   149.4 1398.14   159.4 1398.57   169.5 1398.83   179.5 1398.98   189.5 1399.03
   229.6 1398.75   239.6 1398.84   249.6  1399.1   259.7 1399.54   269.7 1400.23
   279.7 1401.25   289.7 1402.58
#Mann= 3 , 0 , 0
       0     .06       0   104.3    .045       0   114.3     .06       0
Bank Sta=104.3,114.3
XS Rating Curve= 0 ,0
Exp/Cntr=0.3,0.1

Type RM Length L Ch R = 1 ,4566.4  ,184.4,187.2,189.9
XS GIS Cut Line= 2
     1787535.917      180163.474     1787334.193      180207.601
#Sta/Elev= 23
     9.8 1405.75    19.7 1403.68    29.5 1401.72    39.3 1399.83    49.2 1397.93
      59 1395.88    68.8 1393.49    78.7 1391.32    83.5 1390.77    88.5  1390.2
    93.5 1390.23    98.3 1390.26   108.2 1391.49     118 1393.27   127.8 1394.57
   137.7 1395.44   147.5 1396.23   157.3 1397.12   167.2 1398.14     177 1399.19
   186.8 1400.15   196.7 1401.16   206.5 1403.08
#Mann= 3 , 0 , 0
       0     .06       0    83.5    .045       0    93.5     .06       0
Bank Sta=83.5,93.5
XS Rating Curve= 0 ,0
Exp/Cntr=0.3,0.1

Type RM Length L Ch R = 1 ,4379.2  ,106.9,107.2,107.5
XS GIS Cut Line= 4
     1787616.066      180037.397     1787468.376      180011.281
     1787354.906      180016.684     1787267.553      180067.115
#Sta/Elev= 30
      10 1412.79      40 1410.87      60 1409.29      70 1408.16      80  1406.8
      90  1405.2     100 1403.05     110 1400.33     130 1394.33     140 1392.43
     150  1391.7   168.9 1390.98   178.4 1389.92   187.8 1388.19   197.3 1386.63
   201.8 1386.31   206.8 1385.96   211.8 1386.17   216.2 1386.35   225.7 1387.73
   244.6 1391.51   263.6 1394.41   273.7 1396.88   283.8 1401.07   293.8 1406.01
   303.9 1411.28   324.1 1422.24   334.2 1427.92   344.3 1433.66   364.4 1445.39
#Mann= 3 , 0 , 0
       0     .06       0   201.8    .045       0   211.8     .06       0
Bank Sta=201.8,211.8
XS Rating Curve= 0 ,0
Exp/Cntr=0.3,0.1

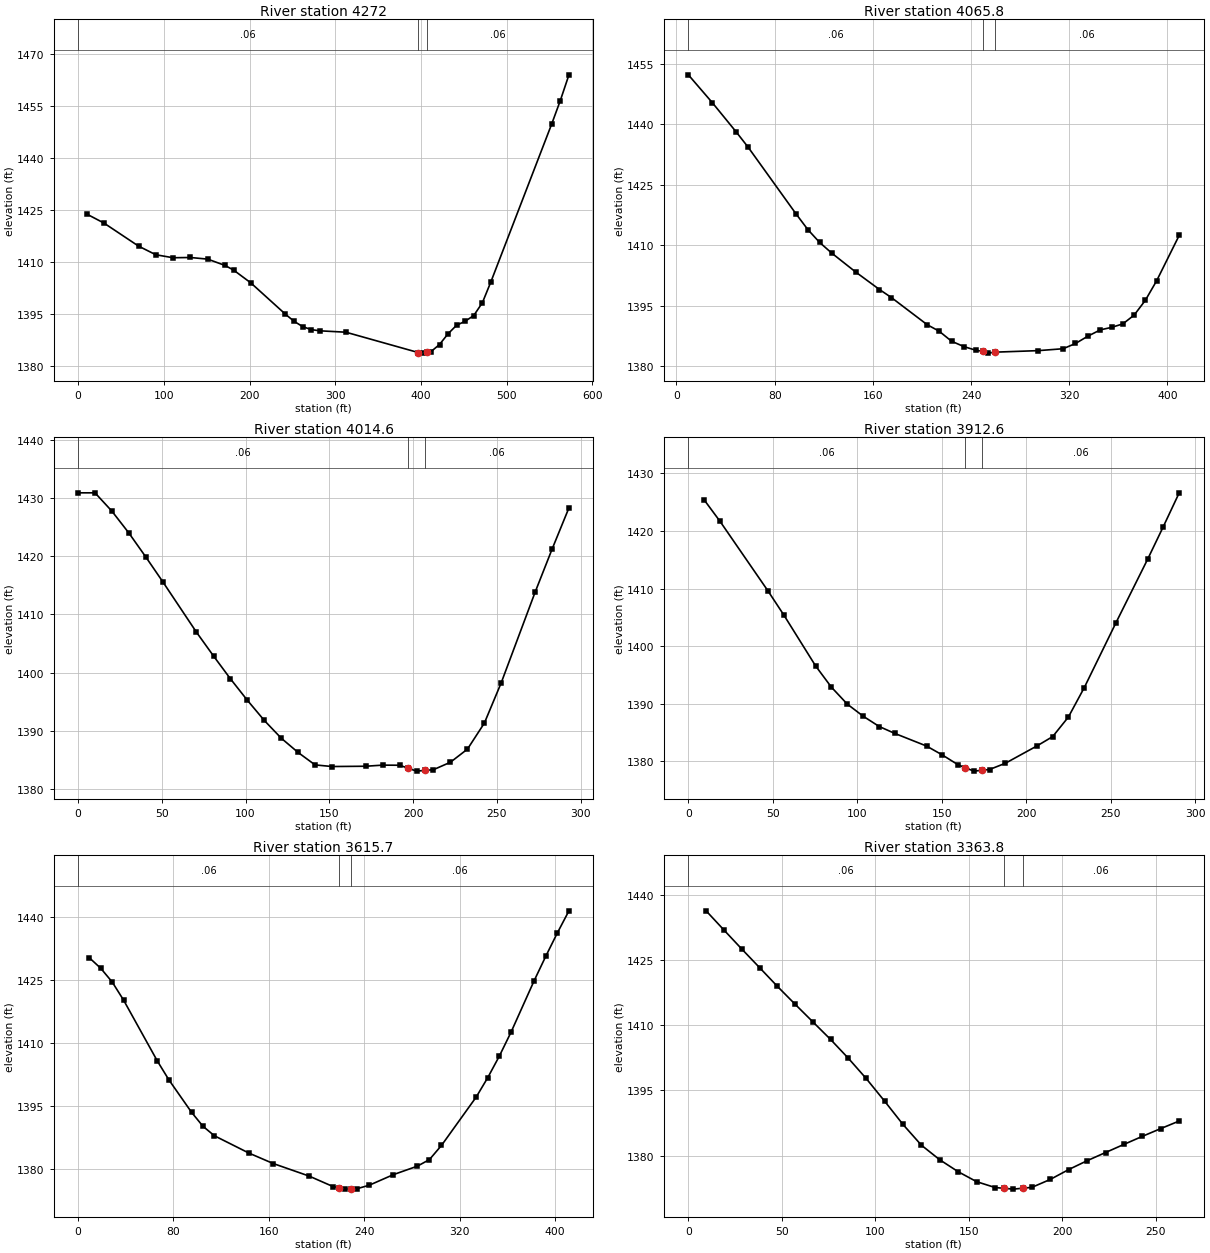
Type RM Length L Ch R = 1 ,4272    ,222.6,206.2,189.9
XS GIS Cut Line= 4
     1787754.751      180035.596     1787457.569      179910.419
      1787328.79      179916.723     1787237.835      179996.872
#Sta/Elev= 30
    10.1 1423.81    30.2 1421.21    70.5 1414.56    90.7 1412.06   110.8  1411.2
     131 1411.27   151.2  1410.8   171.3 1408.99   181.4 1407.64   201.5 1403.94
   241.9 1394.89   251.9 1392.86     262 1391.31   272.1 1390.44   282.2  1390.1
   312.4  1389.7   396.8 1383.83   401.8 1383.66   406.8 1383.88   411.7  1384.1
   421.6 1386.15   431.6 1389.25   441.5  1391.7   451.4 1392.85   461.5  1394.5
   471.6  1398.2   481.7 1404.34   552.4 1449.76   562.5 1456.56   572.6 1464.01
#Mann= 3 , 0 , 0
       0     .06       0   396.8    .045       0   406.8     .06       0
Bank Sta=396.8,406.8
XS Rating Curve= 0 ,0
Exp/Cntr=0.3,0.1

Type RM Length L Ch R = 1 ,4065.8  ,49.5,51.2,52.9
XS GIS Cut Line= 4
     1787549.425      179606.033       1787344.1       179666.37
     1787255.846      179763.629     1787239.636      179825.767
#Sta/Elev= 30
     9.7 1452.32    29.2 1445.42    48.6 1438.18    58.4 1434.36    97.3 1417.86
     107 1413.93   116.7 1410.71   126.5 1408.08   145.9 1403.41   165.4 1399.04
   175.1 1397.05   204.3  1390.3     214  1388.7   224.1 1386.21   234.2 1384.87
   244.3 1383.93   249.4 1383.71  254.19 1383.25   259.4 1383.49   294.8 1383.87
     315 1384.34   325.1 1385.64   335.2 1387.46   345.3 1389.02   354.5 1389.64
   363.7 1390.51   372.9 1392.69     382 1396.35   391.2  1401.2   409.6 1412.48
#Mann= 3 , 0 , 0
     9.7     .06       0   249.4    .045       0   259.4     .06       0
Bank Sta=249.4,259.4
XS Rating Curve= 0 ,0
Exp/Cntr=0.3,0.1

Type RM Length L Ch R = 1 ,4014.6  ,103.3,102,100.7
XS GIS Cut Line= 2
     1787379.262      179572.836     1787170.518      179778.581
#Sta/Elev= 29
       0 1430.88    10.1 1430.88    20.2 1427.73    30.3 1423.99    40.4 1419.88
    50.5 1415.64    70.7 1406.94    80.9 1402.85      91 1398.93   101.1 1395.25
   111.2 1391.79   121.3 1388.75   131.4 1386.29   141.5 1384.16   151.6 1383.88
   171.8 1383.93   181.9 1384.12     192  1384.1   197.1 1383.59   202.1 1383.09
   207.1 1383.21   212.2 1383.34   222.3 1384.61   232.5 1386.87   242.6 1391.34
   252.7 1398.29   272.9 1413.82     283 1421.19   293.1  1428.3
#Mann= 3 , 0 , 0
       0     .06       0   197.1    .045       0   207.1     .06       0
Bank Sta=197.1,207.1
XS Rating Curve= 0 ,0
Exp/Cntr=0.3,0.1

Type RM Length L Ch R = 1 ,3912.6  ,286.1,296.9,307.7
XS GIS Cut Line= 4
     1787306.276       179536.69      1787214.42      179602.431
     1787136.072       179682.58     1787118.061      179745.618
#Sta/Elev= 26
     9.4  1425.4    18.8 1421.67    47.1 1409.62    56.5 1405.43    75.3 1396.59
    84.7 1392.88    94.1 1389.94   103.5 1387.84     113 1386.05   122.3 1384.84
     141 1382.66   150.3 1381.12   159.7  1379.4     164 1378.89     169  1378.3
     174 1378.45   178.3 1378.58   187.7 1379.67   206.4 1382.68   215.7  1384.3
     225  1387.7   234.4 1392.81   253.1 1404.04   271.9  1415.1   281.2 1420.78
   290.6 1426.64
#Mann= 3 , 0 , 0
       0     .06       0     164    .045       0     174     .06       0
Bank Sta=164,174
XS Rating Curve= 0 ,0
Exp/Cntr=0.3,0.1

Type RM Length L Ch R = 1 ,3615.7  ,258.8,251.9,245
XS GIS Cut Line= 4
     1787241.437      179407.912     1787108.155      179409.713
     1786941.553      179450.237     1786881.216      179538.491
#Sta/Elev= 30
     9.5 1430.28      19 1427.79    28.6 1424.52    38.1 1420.23    66.6 1405.62
    76.2 1401.17    95.2 1393.44   104.7 1390.13   114.3 1387.86   143.4 1383.71
   163.6 1381.24   193.8 1378.24     214 1375.72   219.1 1375.42   224.1 1375.13
   229.1 1375.19   234.2 1375.25   244.2 1376.06   264.4 1378.58   284.6 1380.61
   294.7 1382.18   304.8 1385.55   333.9 1397.08   343.6 1401.71   353.3 1406.84
   363.1 1412.54   382.5 1424.82   392.2 1430.62   401.9 1436.18   411.7 1441.49
#Mann= 3 , 0 , 0
       0     .06       0   219.1    .045       0   229.1     .06       0
Bank Sta=219.1,229.1
XS Rating Curve= 0 ,0
Exp/Cntr=0.3,0.1

Type RM Length L Ch R = 1 ,3363.8  ,566.3,559.8,553.7
XS GIS Cut Line= 3
     1787072.254      179106.482     1787015.398      179182.774
     1786873.111      179271.028
#Sta/Elev= 29
     9.5 1436.36      19 1431.96    28.5  1427.6    38.1 1423.28    47.6 1418.98
    57.1 1414.85    66.6 1410.79    76.1 1406.73    85.6  1402.4    95.1 1397.76
     105 1392.52   114.8 1387.17   124.7 1382.37   134.5 1379.02   144.4 1376.26
   154.2 1373.98   164.1 1372.63   168.9 1372.45   173.9 1372.26   178.9 1372.47
   183.8 1372.67   193.6 1374.49   203.5 1376.77   213.3  1378.8   223.2 1380.69
     233 1382.56   242.9 1384.42   252.7  1386.2   262.6 1387.95
#Mann= 3 , 0 , 0
       0     .06       0   168.9    .045       0   178.9     .06       0
Bank Sta=168.9,178.9
XS Rating Curve= 0 ,0
Exp/Cntr=0.3,0.1

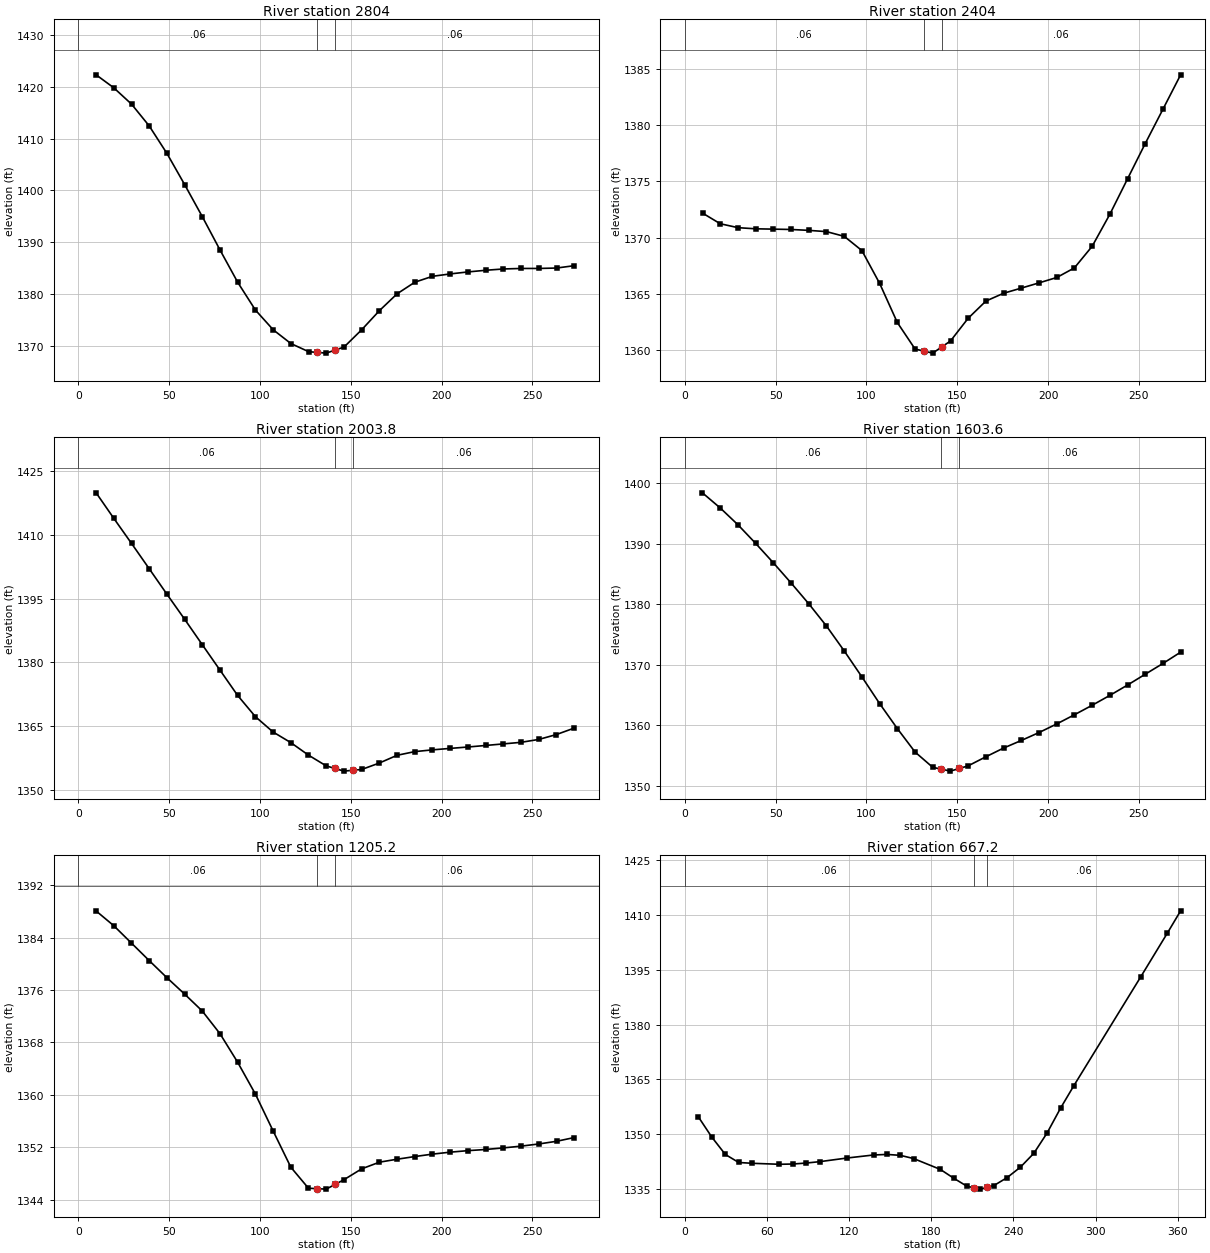
Type RM Length L Ch R = 1 ,2804    ,399.8,400,399.8
XS GIS Cut Line= 3
     1786660.311      178713.834     1786572.645      178818.493
     1786483.223      178921.617
#Sta/Elev= 30
     9.8 1422.25    19.5 1419.76    29.3 1416.61      39 1412.43    48.8 1407.12
    58.5 1401.15    68.3 1394.94      78 1388.56    87.8 1382.31    97.5    1377
   107.3  1373.2     117 1370.56   126.8 1368.99   131.5 1368.85   136.5 1368.71
   141.5 1369.31   146.3 1369.88     156  1373.2   165.8 1376.89   175.5 1380.12
   185.3 1382.36     195 1383.49   204.8 1383.95   214.5 1384.33   224.3 1384.65
     234  1384.9   243.8    1385   253.5    1385   263.3 1385.08     273 1385.53
#Mann= 3 , 0 , 0
       0     .06       0   131.5    .045       0   141.5     .06       0
Bank Sta=131.5,141.5
XS Rating Curve= 0 ,0
Exp/Cntr=0.3,0.1

Type RM Length L Ch R = 1 ,2404    ,398.8,400.1,401.5
XS GIS Cut Line= 3
     1786334.584      178486.613     1786245.924        178590.4
      1786157.52      178694.405
#Sta/Elev= 30
     9.8 1372.17    19.5 1371.23    29.3 1370.88      39 1370.78    48.8 1370.75
    58.5 1370.72    68.3 1370.64      78 1370.53    87.8 1370.11    97.5 1368.85
   107.3 1365.93     117 1362.47   126.8 1360.11   131.5 1359.94   136.5 1359.75
   141.5  1360.3   146.3 1360.83     156 1362.84   165.8 1364.37   175.5 1365.06
   185.3 1365.52     195 1365.98   204.8 1366.46   214.5 1367.31   224.3 1369.23
     234 1372.06   243.8 1375.22   253.5 1378.34   263.3  1381.4     273 1384.44
#Mann= 3 , 0 , 0
       0     .06       0   131.5    .045       0   141.5     .06       0
Bank Sta=131.5,141.5
XS Rating Curve= 0 ,0
Exp/Cntr=0.3,0.1

Type RM Length L Ch R = 1 ,2003.8  ,401.5,400.2,398.9
XS GIS Cut Line= 3
     1786080.949      178192.295     1785985.742      178290.111
     1785890.535      178387.926
#Sta/Elev= 30
     9.8  1419.9    19.5 1413.91    29.3 1407.98      39 1402.04    48.7 1396.08
    58.5 1390.15    68.2 1384.17      78 1378.15    87.7  1372.2    97.5 1367.19
   107.2 1363.59     117 1361.08   126.7 1358.14   136.5  1355.6   141.2 1355.01
   146.2 1354.37   151.2 1354.57     156 1354.76   165.7 1356.27   175.5  1358.1
   185.2 1358.96     195 1359.38   204.7 1359.72   214.5 1360.05   224.2 1360.41
     234 1360.78   243.7 1361.15   253.5 1361.83   263.2 1362.98     273  1364.5
#Mann= 3 , 0 , 0
       0     .06       0   141.2    .045       0   151.2     .06       0
Bank Sta=141.2,151.2
XS Rating Curve= 0 ,0
Exp/Cntr=0.3,0.1

Type RM Length L Ch R = 1 ,1603.6  ,401.2,398.4,395.3
XS GIS Cut Line= 3
     1785760.524      177940.809     1785671.776       178044.52
     1785583.027       178148.23
#Sta/Elev= 30
     9.7 1398.42    19.5 1395.92    29.2 1393.16      39 1390.07    48.8 1386.84
    58.5 1383.53    68.3 1380.07      78 1376.41    87.7 1372.33    97.5 1368.01
   107.3 1363.58     117 1359.47   126.8 1355.58   136.5 1353.06   141.2 1352.76
   146.2 1352.43   151.2 1352.87     156  1353.3   165.7 1354.79   175.5 1356.24
   185.3  1357.5     195  1358.8   204.8 1360.23   214.5 1361.74   224.2  1363.3
     234 1364.94   243.8 1366.66   253.5 1368.44   263.3 1370.23     273 1372.09
#Mann= 3 , 0 , 0
       0     .06       0   141.2    .045       0   151.2     .06       0
Bank Sta=141.2,151.2
XS Rating Curve= 0 ,0
Exp/Cntr=0.3,0.1

Type RM Length L Ch R = 1 ,1205.2  ,542.6,538,533.9
XS GIS Cut Line= 3
      1785433.94       177683.34     1785360.746      177798.554
      1785289.07      177914.738
#Sta/Elev= 30
     9.7 1388.12    19.5 1385.85    29.2  1383.2      39 1380.52    48.7 1377.92
    58.5  1375.4    68.2 1372.82      78 1369.34    87.7 1364.99    97.5 1360.11
   107.2 1354.51     117 1348.94   126.7 1345.73   131.5 1345.66   136.5 1345.59
   141.5 1346.33   146.2 1347.02     156 1348.69   165.8 1349.71   175.5 1350.16
   185.3 1350.57     195 1350.94   204.8 1351.24   214.5 1351.47   224.3 1351.65
     234 1351.89   243.8 1352.16   253.5 1352.49   263.3  1352.9     273 1353.47
#Mann= 3 , 0 , 0
       0     .06       0   131.5    .045       0   141.5     .06       0
Bank Sta=131.5,141.5
XS Rating Curve= 0 ,0
Exp/Cntr=0.3,0.1

Type RM Length L Ch R = 1 ,667.2   ,209.9,221.5,232.5
XS GIS Cut Line= 3
     1784928.821      177554.577     1784858.578      177661.743
     1784799.364      177888.097
#Sta/Elev= 30
     9.9 1354.71    19.7 1349.17    29.6  1344.4    39.4  1342.2    49.3 1341.98
      69 1341.71    78.9 1341.78    88.7 1342.05    98.6 1342.43   118.3 1343.42
   137.9 1344.26   147.6 1344.41   157.4 1344.16   167.1 1343.28   186.6 1340.31
   196.4 1337.89   206.1 1335.68   210.9  1335.3   215.9  1334.9   220.9 1335.39
   225.6 1335.85   235.4 1338.06   245.1 1340.92   254.9 1344.72   264.6  1350.3
   274.4 1357.09   284.1 1363.24   332.9 1393.04   352.4 1405.07   362.1 1411.18
#Mann= 3 , 0 , 0
       0     .06       0   210.9    .045       0   220.9     .06       0
Bank Sta=210.9,220.9
XS Rating Curve= 0 ,0
Exp/Cntr=0.3,0.1

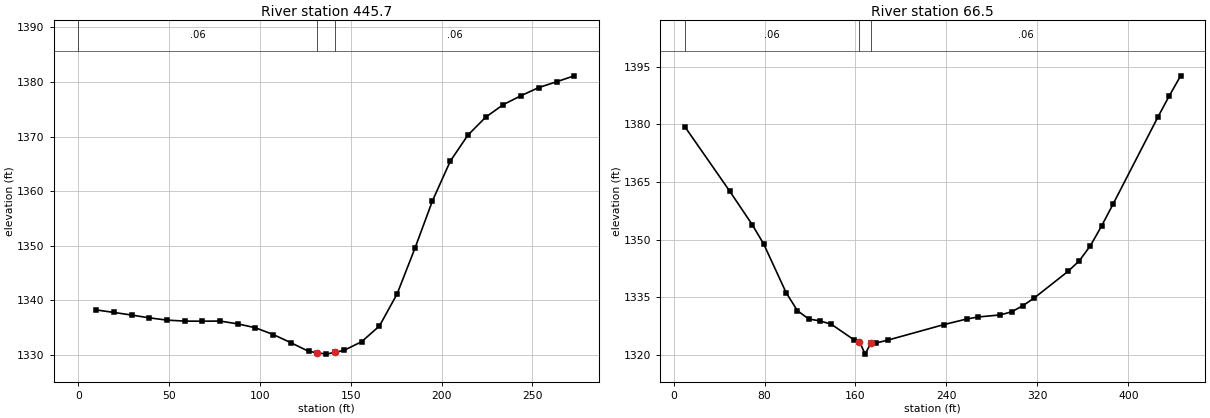
Type RM Length L Ch R = 1 ,445.7   ,393.6,379.3,365.2
XS GIS Cut Line= 3
     1784787.163      177530.986     1784680.073      177615.648
     1784574.074      177701.647
#Sta/Elev= 30
     9.8 1338.24    19.5 1337.78    29.3  1337.3      39 1336.79    48.8 1336.37
    58.5 1336.19    68.3 1336.17      78  1336.2    87.8 1335.68    97.5 1334.97
   107.3 1333.73     117 1332.24   126.8 1330.65   131.5  1330.4   136.5 1330.14
   141.5 1330.49   146.3 1330.83     156 1332.42   165.8  1335.3   175.5 1341.16
   185.3  1349.5     195 1358.24   204.8 1365.49   214.5 1370.26   224.3 1373.55
     234 1375.85   243.8 1377.49   253.5 1378.97   263.3 1380.03     273 1381.12
#Mann= 3 , 0 , 0
       0     .06       0   131.5    .045       0   141.5     .06       0
Bank Sta=131.5,141.5
XS Rating Curve= 0 ,0
Exp/Cntr=0.3,0.1

Type RM Length L Ch R = 1 ,66.5    ,75.1,66.5,57.9
XS GIS Cut Line= 2
     1784478.843       177186.44     1784387.144      177622.869
#Sta/Elev= 30
     9.9 1379.37    49.6  1362.5    69.4 1353.78    79.3 1348.84    99.1 1336.14
     109 1331.49   118.9 1329.34   128.8 1328.84   138.7 1327.98   158.6 1323.95
   163.5 1323.48   168.5  1320.2   173.5 1323.05   178.4 1323.11   188.3 1323.83
   237.8 1327.88   257.7 1329.32   267.6 1329.85   287.4  1330.4   297.3  1331.2
   307.2 1332.79   317.1 1334.77   346.9 1341.71   356.8 1344.44   366.7 1348.42
   376.6 1353.59   386.5 1359.17   426.1 1381.91     436 1387.36     446 1392.58
#Mann= 3 , 0 , 0
     9.9     .06       0   163.5    .045       0   173.5     .06       0
Bank Sta=163.5,173.5
XS Rating Curve= 0 ,0
Exp/Cntr=0.3,0.1

Chan Stop Cuts=-1
Use User Specified Reach Order=0